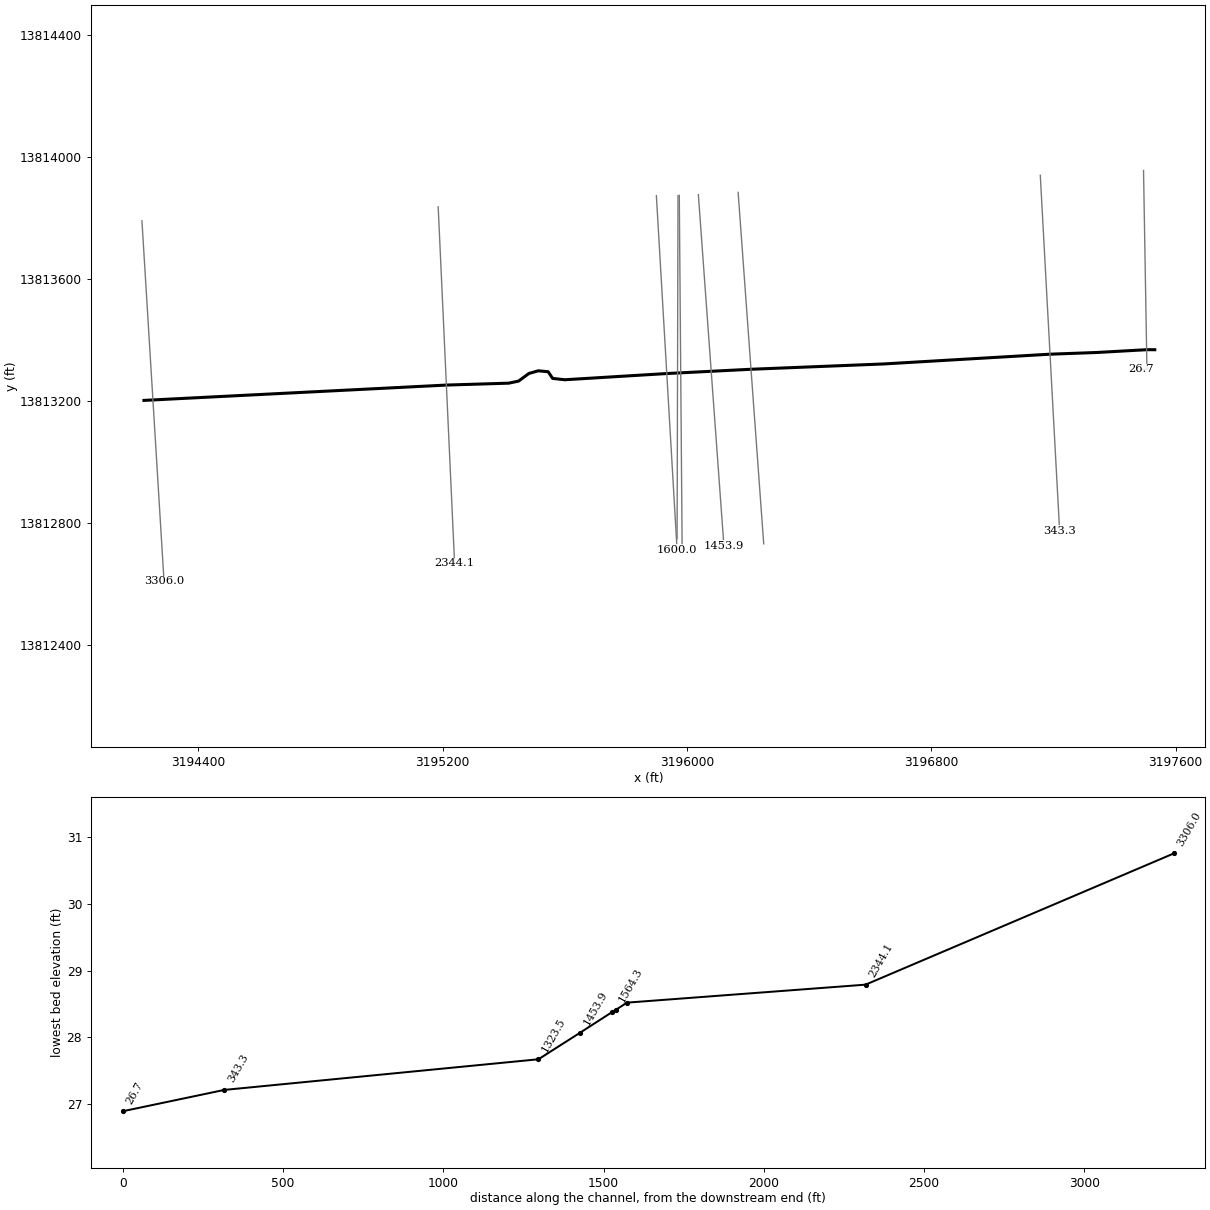
--- B114-01-00.prj (project) ---

Proj Title=B114-01-00
Current Plan=p09
Default Exp/Contr=.3,.1
English Units
Geom File=g02
Flow File=f04
Flow File=f01
Plan File=p09
Plan File=p01
Y Axis Title=Elevation
X Axis Title(PF)=Main Channel Distance
X Axis Title(XS)=Station
BEGIN DESCRIPTION:
Watershed: Armand Bayou
Stream name:
HCFCD Unit B114-01-00
(Flood Hazard, Floodway) Model
10. 2 1 0.2% Event
Filename: B114-01-00.prj
Prepared by: Ty Turner 2-2003, Revised by Sean Sutton 6-10-2003
Reviewed by:
STATUS: Final RAS
END DESCRIPTION:
DSS File=dss
DSS Export Rating Curves= 0
DSS Export Rating Curve Sorted= 0
DSS Export Volume Flow Curves= 0
DXF OffsetX= 0
DXF OffsetY= 0
DXF ScaleX= 1
DXF ScaleY= 10

--- B114-01-00.p09 (plan) ---

Plan Title=FEMA Effective June 2007
Version=Version 3.0.1  Mar 2001
Short Identifier=FEMAeff0607
Geom File=g02
Flow File=f04
Subcritical Flow
K Sum by GR= 0
Std Step Tol= 0.01
Critical Tol= 0.01
Num of Std Step Trials= 20
Max Error Tol= 0.3
Flow Tol Ratio= 0.001
Split Flow NTrial= 30
Split Flow Tol= 0.02
Split Flow Ratio= 0.02
Log Output Level= 0
Friction Slope Method= 0
Unsteady Friction Slope Method= 2
Secant Critical Depth
Global Vel Dist= 0 , 0 , 0
Global Log Level= 0
CheckData=True
Encroach Param=-1 ,0,0, 2
BEGIN DESCRIPTION:
Flood Hazard Run
END DESCRIPTION:
Computation Interval=1HOUR
Output Interval=1HOUR
Run HTab= 0
Run UNet= 0
Run PostProcess= 0
UNET Theta= 1
UNET ZTol= 0.02
UNET ZSATol= 0.1
UNET MxIter= 20
UNET MaxInSteps= 20
UNET DtIC= 0
UNET DtMin= 0
UNET MaxCRTS= 20
UNET WFStab= 2
UNET SFStab= 1
UNET WFX= 1
UNET SFX= 1
UNET Convert EG Bridges=-1
UNET Use Existing IB Tables=-1
Instantaneous Interval=1HOUR
Write IC File= 0
IC Time=0
Write Velocity= 0
Write Detailed= 0

--- B114-01-00.p01 (plan) ---

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Plan Title=Floodway
Geom File=g02
Flow File=f01
Encroach River=B114-01-00
Encroach Reach=1
Encroach Node=3306.0
       1  572.26   600.7
Encroach Node=2344.1
       1   567.6  601.54
Encroach Node=1600.0
       1   563.7  604.07
Encroach Node=1564.3
       1   563.7  603.77
Encroach Node=1560
       1   563.7  603.77
Encroach Node=1553.8
       1   563.7  603.77
Encroach Node=1453.9
       1  565.12  607.85
Encroach Node=1323.5
       1  565.12  607.45
Encroach Node=343.3
       1  571.24  605.14
Encroach Node=26.7
       1  564.12  614.03
Encroach Reach=B114-01-00_0000
Encroach Node=3306.0
       1  572.26   600.7
Encroach Node=2344.1
       1   567.6  601.54
Encroach Node=1600.0
       1   563.7  604.07
Encroach Node=1564.3
       1   563.7  603.77
Encroach Node=1560
       1   563.7  603.77
Encroach Node=1553.8
       1   563.7  603.77
Encroach Node=1453.9
       1  565.12  607.85
Encroach Node=1323.5
       1  565.12  607.45
Encroach Node=343.3
       1  571.24  605.14
Encroach Node=26.7
       1  564.12  614.03
Flood Encroachment Run
DSS File=dss

--- B114-01-00.f04 (steady flow) ---

Flow Title=FEMA Effective June 2007
Version=Version 3.0.1  Mar 2001
Number of Profiles= 4
Profile Names=10PCT_10yr, 2PCT_50yr, 1PCT_100yr, 0.2PCT_500yr
River Rch & RM=B114-01-00,B114-01-00_0000               ,3306.0
       6       8       9      13
River Rch & RM=B114-01-00,B114-01-00_0000               ,2344.1
      26      37      43      61
River Rch & RM=B114-01-00,B114-01-00_0000               ,1600.0
      41      60      69      97
River Rch & RM=B114-01-00,B114-01-00_0000               ,1453.9
      44      64      74     104
River Rch & RM=B114-01-00,B114-01-00_0000               ,1323.5
      47      68      79     111
River Rch & RM=B114-01-00,B114-01-00_0000               ,343.3
      67      98     113     159
River Rch & RM=B114-01-00,B114-01-00_0000               ,26.7
      74     107     125     175
Boundary for River Rch & Prof#=B114-01-00,B114-01-00_0000               , 1
Up Type= 0
Dn Type= 3
Dn Slope=.001
Boundary for River Rch & Prof#=B114-01-00,B114-01-00_0000               , 2
Up Type= 0
Dn Type= 3
Dn Slope=.001
DSS Import GetInterval= 0
DSS Import GetPeak= 0
DSS Import FillOption= 0

--- B114-01-00.f01 (steady flow) ---

Flow Title=Floodway
Version=Version 3.0.1  Mar 2001
Number of Profiles= 2
Profile Names=1PCT_100yr, 1PCTFloodway_100yrFW
River Rch & RM=B114-01-00,B114-01-00_0000               ,3306.0
       9       9
River Rch & RM=B114-01-00,B114-01-00_0000               ,2344.1
      43      43
River Rch & RM=B114-01-00,B114-01-00_0000               ,1600.0
      69      69
River Rch & RM=B114-01-00,B114-01-00_0000               ,1453.9
      74      74
River Rch & RM=B114-01-00,B114-01-00_0000               ,1323.5
      79      79
River Rch & RM=B114-01-00,B114-01-00_0000               ,343.3
     113     113
River Rch & RM=B114-01-00,B114-01-00_0000               ,26.7
     125     125
Boundary for River Rch & Prof#=B114-01-00,B114-01-00_0000               , 1
Up Type= 0
Dn Type= 3
Dn Slope=.001
Boundary for River Rch & Prof#=B114-01-00,B114-01-00_0000               , 2
Up Type= 0
Dn Type= 3
Dn Slope=.001
DSS Import GetInterval= 0
DSS Import GetPeak= 0
DSS Import FillOption= 0

--- B114-01-00.g02 (geometry) ---

Geom Title=B114-01-00 June 2007
Version=Version 3.0.1  Mar 2001

River Reach=B114-01-00      ,B114-01-00_0000
Reach XY= 30
     3194222.628    13813201.404     3194236.645    13813202.115
      3194600.45    13813220.591     3194678.858    13813224.574
     3194693.133    13813225.298     3194716.645    13813226.493
     3194774.278    13813229.419     3195212.596     13813251.68
      3195416.74     13813257.92     3195448.964     13813264.73
     3195482.702    13813289.667     3195513.505    13813298.468
     3195545.776    13813295.534     3195560.445    13813273.531
      3195600.05    13813269.131     3195934.139    13813289.508
     3195934.318    13813289.518      3196210.23    13813303.561
     3196351.645    13813309.232     3196464.666    13813313.766
     3196471.645    13813314.045     3196565.617    13813317.815
     3196591.645    13813318.858     3196642.958    13813320.917
     3197188.783    13813352.976     3197342.667    13813358.609
     3197475.943    13813366.084     3197504.949    13813367.712
     3197505.963    13813367.768     3197531.689    13813367.661

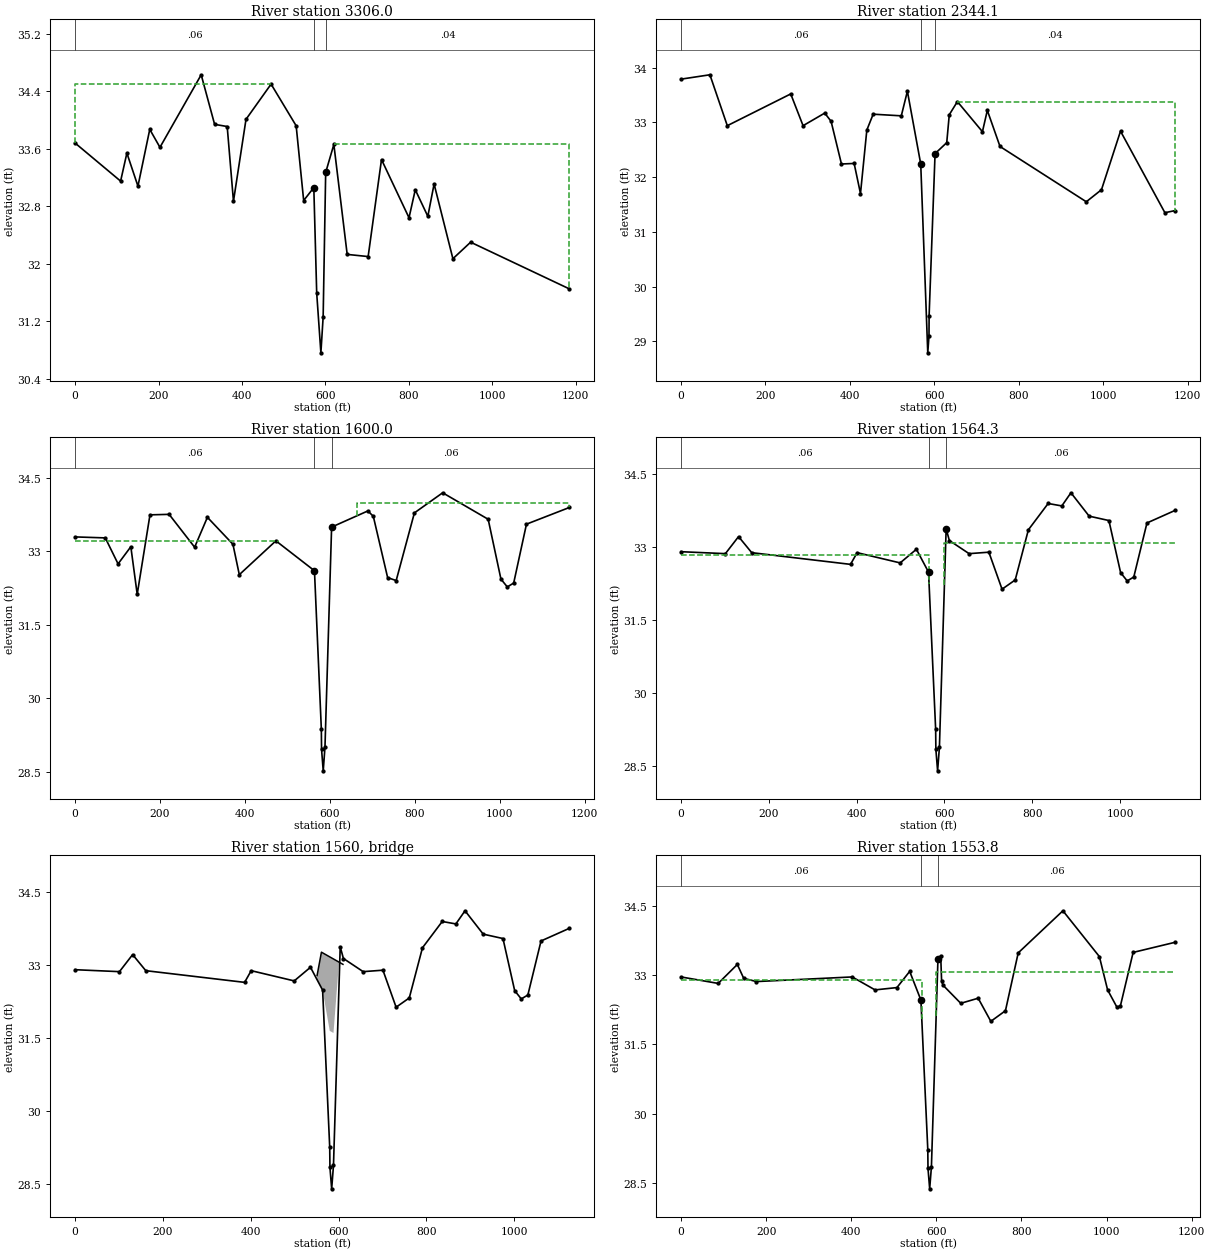
Type RM Length L Ch R = 1 ,3306.0  ,962.39,961.96,961.58
BEGIN DESCRIPTION:
B114-01-00-v1 (Survey 547.93 to 620.29)
END DESCRIPTION:
XS GIS Cut Line= 4
     3194215.969    13813790.748       3194246.5    13813291.681
     3194257.785     13813107.22     3194288.316    13812608.153
#Sta/Elev= 30
       0   33.68  109.16   33.15  124.19   33.54  150.72   33.08  179.04   33.87
  203.47   33.62  302.31   34.63  334.46   33.94  364.64   33.91  379.67   32.87
  409.73   34.01  469.84    34.5  529.95   33.92  547.93   32.88  572.26   33.06
   579.2   31.59  589.22   30.76  594.64   31.26   600.7   33.27  620.29   33.66
  652.25   32.13  702.49    32.1  734.51   33.45  800.45   32.64  815.48   33.03
  845.54   32.66  860.57   33.11  905.65   32.07  948.14    32.3 1184.81   31.65
#Mann= 3 , 0 , 0
       0     .06       0  572.26     .04       0   600.7     .04       0
#XS Ineff= 2 , 0
       0  469.84    34.5  620.29       0   33.66
Permanent Ineff=
       F       F
Bank Sta=572.26,600.7
XS Rating Curve= 0
Exp/Cntr=.3,.1

Type RM Length L Ch R = 1 ,2344.1  ,740.85,744.52,725.56
BEGIN DESCRIPTION:
B114-01-00-v2 (Survey 536.01 to 629.17)
END DESCRIPTION:
XS GIS Cut Line= 4
     3195185.805    13813836.294      3195208.74     13813336.82
     3195216.552    13813166.681     3195239.487    13812667.208
#Sta/Elev= 30
       0   33.79   68.43   33.87  109.62   32.94  259.78   33.52  289.01   32.94
  340.33   33.17  355.34   33.02  379.91   32.24  409.94   32.25  424.95    31.7
  439.97   32.86  454.99   33.15   521.6   33.12  536.01   33.57   567.6   32.24
  584.26   28.79  587.15    29.1  587.44   29.47  601.54   32.43  629.17   32.63
  635.18   33.14  654.37   33.38  713.71   32.83  725.27   33.22   755.3   32.56
   959.6   31.55  995.55   31.77  1040.6   32.84 1145.71   31.35 1170.32   31.39
#Mann= 3 , 0 , 0
       0     .06       0   567.6     .04       0  601.54     .04       0
#XS Ineff= 2 , 0
       0  536.01   33.57  654.37       0   33.38
Permanent Ineff=
       F       F
Bank Sta=567.6,601.54
XS Rating Curve= 0
Exp/Cntr=.3,.1

Type RM Length L Ch R = 1 ,1600.0  ,37.15,35.28,33.33
BEGIN DESCRIPTION:
B114-01-00-s1 XS4
END DESCRIPTION:
XS GIS Cut Line= 4
     3195900.097    13813872.863     3195929.226    13813373.713
     3195938.774    13813210.084     3195967.902    13812710.933
#Sta/Elev= 30
       0   33.29    71.2   33.27  101.25   32.74   131.3   33.09  146.32   32.12
  176.38   33.74  221.45   33.75  281.55   33.08  311.61   33.69  371.71   33.14
  386.73   32.52  472.88   33.21   563.7    32.6  579.89   29.37  580.38   28.96
  584.32   28.52  588.43      29  604.07   33.49  689.49   33.82  702.27   33.71
     736   32.46  756.11    32.4  799.01   33.78  865.61   34.19  972.73   33.65
 1002.78   32.43  1017.8   32.27 1032.83   32.35 1062.88   33.55 1163.91   33.89
#Mann= 3 , 0 , 0
       0     .06       0   563.7     .04       0  604.07     .06       0
#XS Ineff= 2 , 0
       0  476.89   33.21  664.53       0   33.98
Permanent Ineff=
       F       F
Bank Sta=563.7,604.07
XS Rating Curve= 0
Exp/Cntr=.5,.3

Type RM Length L Ch R = 1 ,1564.3  ,10.11,10.45,10.79
BEGIN DESCRIPTION:
Survey data copied from 1600.0 (561.14-610.22) (-0.11) XS3
END DESCRIPTION:
XS GIS Cut Line= 4
     3195970.938    13813872.843      3195969.59    13813372.845
     3195969.156     13813211.82     3195967.904    13812747.253
#Sta/Elev= 30
       0   32.91  101.06   32.87  131.06   33.22  161.06   32.89  386.06   32.65
  401.06   32.89  499.01   32.68  536.06   32.96   563.7   32.49  579.89   29.26
  580.38   28.85  584.32   28.41  588.44   28.89  603.77   33.38  611.06   33.14
  656.06   32.87  701.06    32.9  731.06   32.14  761.06   32.33  791.06   33.36
  836.06    33.9  867.15   33.85  887.96   34.12  929.45   33.64  974.39   33.55
 1001.06   32.48 1016.06   32.31 1031.06   32.39 1061.06    33.5 1125.59   33.76
#Mann= 3 , 0 , 0
       0     .06       0   563.7     .04       0  603.77     .06       0
#XS Ineff= 2 , 0
       0   564.9   32.85  599.84       0   33.08
Permanent Ineff=
       F       F
Bank Sta=563.7,603.77
XS Rating Curve= 0
Exp/Cntr=.5,.3

Type RM Length L Ch R = 3 ,1560    ,,,
BEGIN DESCRIPTION:
Wakeshire Rd.
END DESCRIPTION:
Bridge Culvert--1,0,-1,-1, 0
Deck Dist Width WeirC Skew NumUp NumDn MinLoCord MaxHiCord MaxSubmerge Is_Ogee
2,6,2.6,0, 3, 3, 33.27, , .95, 0, 0,0,,
  551.06     561     610
   32.79   33.27   33.02
      32   31.75    31.5
  552.36     561     610
    32.9   33.27      33
      32   31.75    31.5
BR Coef=-1 , 1 , 0 ,, 0 ,,,.8,0,1.2,0,
WSPro=,,,, 1 ,,,, 0 ,,,, 0 ,,,,-1 ,-1 ,-1 , 0 , 0 , 0 , 0 , 0
BC Design=,, 0 ,, 0 ,,,,,,

Type RM Length L Ch R = 1 ,1553.8  ,98.02,99.94,102.06
BEGIN DESCRIPTION:
Survey data (561.14-610.22) copied from 1600.0 (-0.14) XS2
END DESCRIPTION:
XS GIS Cut Line= 4
     3195975.107     13813874.13     3195979.139    13813374.147
     3195980.441    13813212.688     3195984.473    13812712.705
#Sta/Elev= 30
       0   32.96   87.35   32.82  132.35   33.23  147.35   32.93  177.35   32.86
  402.36   32.96  455.93   32.68  507.36   32.73  537.36   33.08   563.7   32.46
  579.89   29.23  580.38   28.82  584.32   28.38  588.44   28.86  603.77   33.35
  610.22   33.42  612.36   32.87  615.79   32.78  657.36   32.39  698.27    32.5
  728.03      32  762.37   32.23  792.37   33.48  897.37   34.39  983.07    33.4
 1002.38   32.68  1024.1   32.31 1032.38   32.33 1062.38   33.49 1161.46   33.71
#Mann= 3 , 0 , 0
       0     .06       0   563.7     .04       0  603.77     .06       0
#XS Ineff= 2 , 0
       0   565.7    32.9  599.59       0   33.06
Permanent Ineff=
       F       F
Bank Sta=563.7,603.77
XS Rating Curve= 0
Exp/Cntr=.5,.3

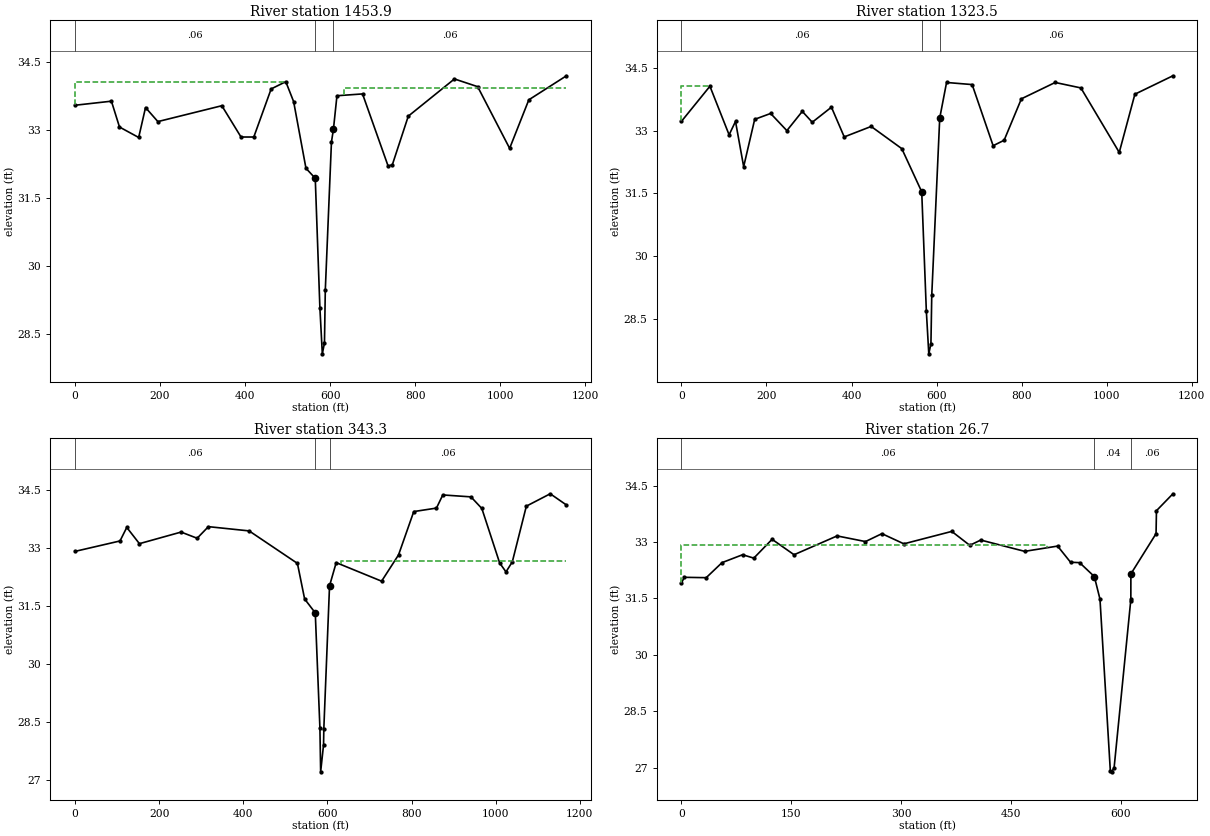
Type RM Length L Ch R = 1 ,1453.9  ,130.48,130.43,130.49
BEGIN DESCRIPTION:
Survey data (543.28-607.45) copied from 1323.5 (+0.4) XS1
END DESCRIPTION:
XS GIS Cut Line= 4
     3196037.539    13813876.305     3196073.757    13813377.619
     3196085.042    13813222.237     3196121.259     13812723.55
#Sta/Elev= 30
       0   33.55    85.8   33.64  104.79   33.07  149.91   32.84     166    33.5
  195.03   33.19  345.43   33.54  390.54   32.85  420.62   32.85  461.41   33.91
  495.82   34.07  514.29   33.63  543.28   32.16  565.12   31.94  575.99   29.09
  581.74   28.07  586.78   28.31  588.72   29.47   603.2   32.74  607.85   33.02
  616.14   33.76  676.29    33.8  736.45   32.21  746.44   32.24   783.9   33.31
   892.4   34.13  947.01   33.96  1022.2    32.6 1067.32   33.67 1155.79    34.2
#Mann= 3 , 0 , 0
       0     .06       0  565.12     .04       0  607.85     .06       0
#XS Ineff= 2 , 0
       0  495.82   34.07  631.58       0   33.93
Permanent Ineff=
       F       F
Bank Sta=565.12,607.85
XS Rating Curve= 0
Exp/Cntr=.3,.1

Type RM Length L Ch R = 1 ,1323.5  ,980.65,980.16,979.5
BEGIN DESCRIPTION:
B114-01-00-v3 (Survey 543.28 to 607.45)
END DESCRIPTION:
XS GIS Cut Line= 4
     3196167.748    13813883.684     3196203.965    13813384.997
      3196215.25    13813229.615     3196251.467    13812730.929
#Sta/Elev= 30
       0   33.22   67.07   34.06  112.19    32.9  127.23   33.22  146.43   32.14
  172.35   33.27  209.84   33.41  248.01      33   284.3   33.46  307.71    33.2
  352.82   33.56   382.9   32.85  446.22    33.1  518.26   32.57  565.12   31.54
  575.99   28.69  581.74   27.67  586.78   27.91  588.72   29.07  607.45    33.3
  623.53   34.15  683.69    34.1  733.02   32.64  758.89   32.77  799.49   33.76
  878.98   34.15  939.36   34.02  1029.6   32.48 1066.37   33.87 1155.79   34.31
#Mann= 3 , 0 , 0
       0     .06       0  565.12     .04       0  607.45     .06       0
#XS Ineff= 2 , 0
       0   67.07   34.06  623.53       0   34.15
Permanent Ineff=
       F       F
Bank Sta=565.12,607.45
XS Rating Curve= 0
Exp/Cntr=.3,.1

Type RM Length L Ch R = 1 ,343.3   ,317.54,316.55,315.76
BEGIN DESCRIPTION:
B114-01-00-v4 (Survey 545.92 to 620.97)
END DESCRIPTION:
XS GIS Cut Line= 4
     3197156.908    13813939.818        3197184.    13813440.553
     3197193.115    13813272.584     3197220.206    13812773.319
#Sta/Elev= 30
       0   32.91  107.12   33.18  123.21   33.53  153.26   33.11  252.34   33.41
  290.46   33.25  317.22   33.55  414.03   33.44  528.81    32.6  545.92   31.68
  571.24   31.32  582.28   28.34     584   27.21  590.93   27.91  591.58   28.33
  605.14   32.02  620.97   32.62  728.86   32.14  769.16   32.82  805.32   33.94
  859.29   34.03  874.32   34.37  941.28   34.32  967.12   34.02 1009.51   32.61
 1024.54   32.38 1039.56   32.64 1072.91   34.08 1129.69    34.4 1168.22   34.11
#Mann= 3 , 0 , 0
       0     .06       0  571.24     .04       0  605.14     .06       0
#XS Ineff= 2 , 0
       0                  631.58       0   32.65
Permanent Ineff=
       F       F
Bank Sta=571.24,605.14
XS Rating Curve= 0
Exp/Cntr=.3,.1

Type RM Length L Ch R = 1 ,26.7    ,25.08,26.74,27.96
BEGIN DESCRIPTION:
B114-01-00-v1 (Survey 564.12 to 648.43)
END DESCRIPTION:
XS GIS Cut Line= 4
     3197494.899    13813955.671     3197503.444    13813455.744
     3197506.049      13813303.4     3197486.951      13813303.4
#Sta/Elev= 30
       0    31.9    3.88   32.06   33.89   32.05   55.49   32.45   83.58   32.66
   98.93   32.57   123.9   33.07  153.91   32.66  212.69   33.16  251.47   33.01
  273.92   33.22  303.93   32.95  369.37   33.28  393.94   32.91  408.94   33.05
  468.95   32.75  513.96   32.89  531.62   32.46  543.96   32.45  564.12   32.08
  571.82   31.48  586.02    26.9  587.96   26.89  591.13      27  613.72   31.42
  613.99   31.48  614.03   32.15  648.43   33.22  648.98   33.83  671.46   34.28
#Mann= 3 , 0 , 0
       0     .06       0  564.12     .04       0  614.03     .06       0
#XS Ineff= 2 , 0
       0  498.96   32.93               0
Permanent Ineff=
       F       F
Bank Sta=564.12,614.03
XS Rating Curve= 0
Exp/Cntr=.3,.1

Chan Stop Cuts=-1